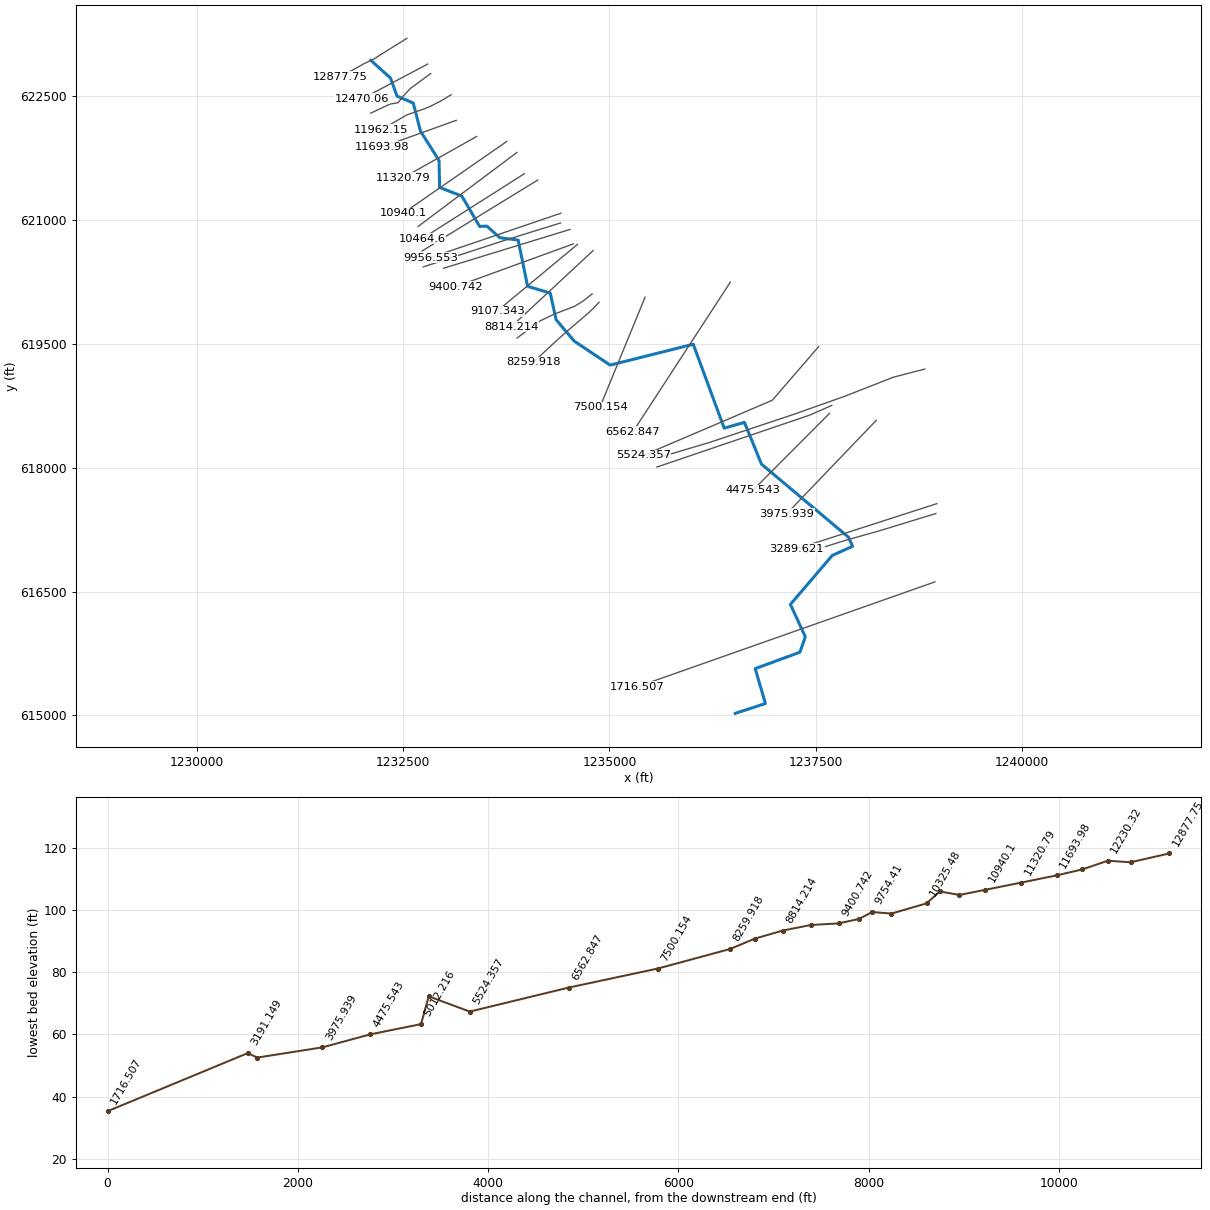
--- 348_ras.prj (project) ---

Proj Title=348
Current Plan=p01
Default Exp/Contr=0.3,0.1
English Units
Geom File=g01
Flow File=f01
Plan File=p01
Y Axis Title=Elevation
X Axis Title(PF)=Main Channel Distance
X Axis Title(XS)=Station
BEGIN DESCRIPTION:
RFD model 348 exported to HEC-RAS
END DESCRIPTION:

--- 348_ras.p01 (plan) ---

Plan Title=Plan 01
Program Version=4.10
Short Identifier=Plan 01
Geom File=g01
Flow File=f01
Subcritical Flow
Calc Critical at every XS
Secant Critical Depth

--- 348_ras.f01 (steady flow) ---

Flow Title=Flow 01
Program Version=5.01
Number of Profiles= 5
Profile Names=10yr,25yr,50yr,100yr,500yr
River Rch & RM=348,28,12877.75
  366.08  433.68  516.21  546.75  635.39
River Rch & RM=348,28,12470.06
  411.17  495.44     592   637.9  757.84
River Rch & RM=348,28,12230.32
  466.58   572.7  687.19  754.44  918.05
River Rch & RM=348,28,11962.15
  554.94  698.64  843.15  949.72 1194.33
River Rch & RM=348,28,11693.98
  576.89  730.39   882.6  999.88  1266.7
River Rch & RM=348,28,11320.79
   592.2  752.66   910.3 1035.26 1318.05
River Rch & RM=348,28, 10940.1
  602.52  767.71  929.04 1059.28 1353.07
River Rch & RM=348,28,10670.56
  683.84  887.59 1078.63 1253.09 1639.53
River Rch & RM=348,28, 10464.6
  695.72  905.29 1100.77 1282.07 1682.94
River Rch & RM=348,28,10325.48
  698.55  909.52 1106.06    1289 1693.35
River Rch & RM=348,28,9956.553
  788.37 1044.77 1275.65 1513.49 2034.41
River Rch & RM=348,28, 9754.41
  809.92 1077.57 1316.87 1568.64 2119.36
River Rch & RM=348,28,9614.921
  831.98 1111.27 1359.27 1625.59 2207.52
River Rch & RM=348,28,9400.742
  834.67 1115.39 1364.46 1632.58 2218.37
River Rch & RM=348,28,9107.343
  851.09 1140.57 1396.16 1675.33  2284.9
River Rch & RM=348,28,8814.214
  854.99 1146.56 1403.71 1685.53 2300.79
River Rch & RM=348,28,8523.918
  881.06 1186.72 1454.32 1754.08 2408.05
River Rch & RM=348,28,8259.918
  891.84 1203.38 1475.34 1782.63 2452.91
River Rch & RM=348,28,7500.154
  929.24  1261.4 1548.57 1882.52 2610.62
River Rch & RM=348,28,6562.847
  1125.8 1571.69 1941.83 2428.55  3492.7
River Rch & RM=348,28,5524.357
 1156.26 1620.52 2003.94 2516.14 3637.04
River Rch & RM=348,28,5092.187
 1171.92 1645.69 2035.98 2561.46 3712.01
River Rch & RM=348,28,1716.507
 1171.28 1644.67 2034.67  2559.6 3708.94
Boundary for River Rch & Prof#=348,28,1
Up Type= 0
Dn Type= 2
Boundary for River Rch & Prof#=348,28,2
Up Type= 0
Dn Type= 2
Boundary for River Rch & Prof#=348,28,2
Up Type= 0
Dn Type= 2
Boundary for River Rch & Prof#=348,28,2
Up Type= 0
Dn Type= 2
Boundary for River Rch & Prof#=348,28,2
Up Type= 0
Dn Type= 2

--- 348_ras.g01 (geometry) ---

Geom Title=348
Program Version=4.10

River Reach=348,28
Reach XY= 30
1232108.75893273622935.6194768821232346.60607857622722.077866706
 1232426.4671597622501.5918187351232622.64765495622418.258504443
1232709.45317505622079.716935768 1232935.1475425621722.078146518
1232942.09197541621395.689354286 1233211.1891152 621291.52271074
1233426.46681874620923.4672582251233515.00845938620926.939476838
1233672.99451978 620786.314513991233893.48056503620758.536738059
1234008.06384824620197.7730123441234282.36932048620116.175806359
1234353.54984563619793.2592335021234572.29977356619534.578748407
1235008.06352537619242.9121556821236015.00768005619496.384273386
1236390.00753979 618479.023453441236635.20174282618549.801151393
1236841.21631242618044.2298266371237896.21597528617157.563392559
1237945.38262425617047.5634237831237700.38269337616938.396796663
1237192.04949275616344.2303212011237372.88276128615950.897099395
1237307.04944197615765.0638231481236765.38292935615565.897231364
1236889.54954709615143.3973532291236523.65743738615023.884548896

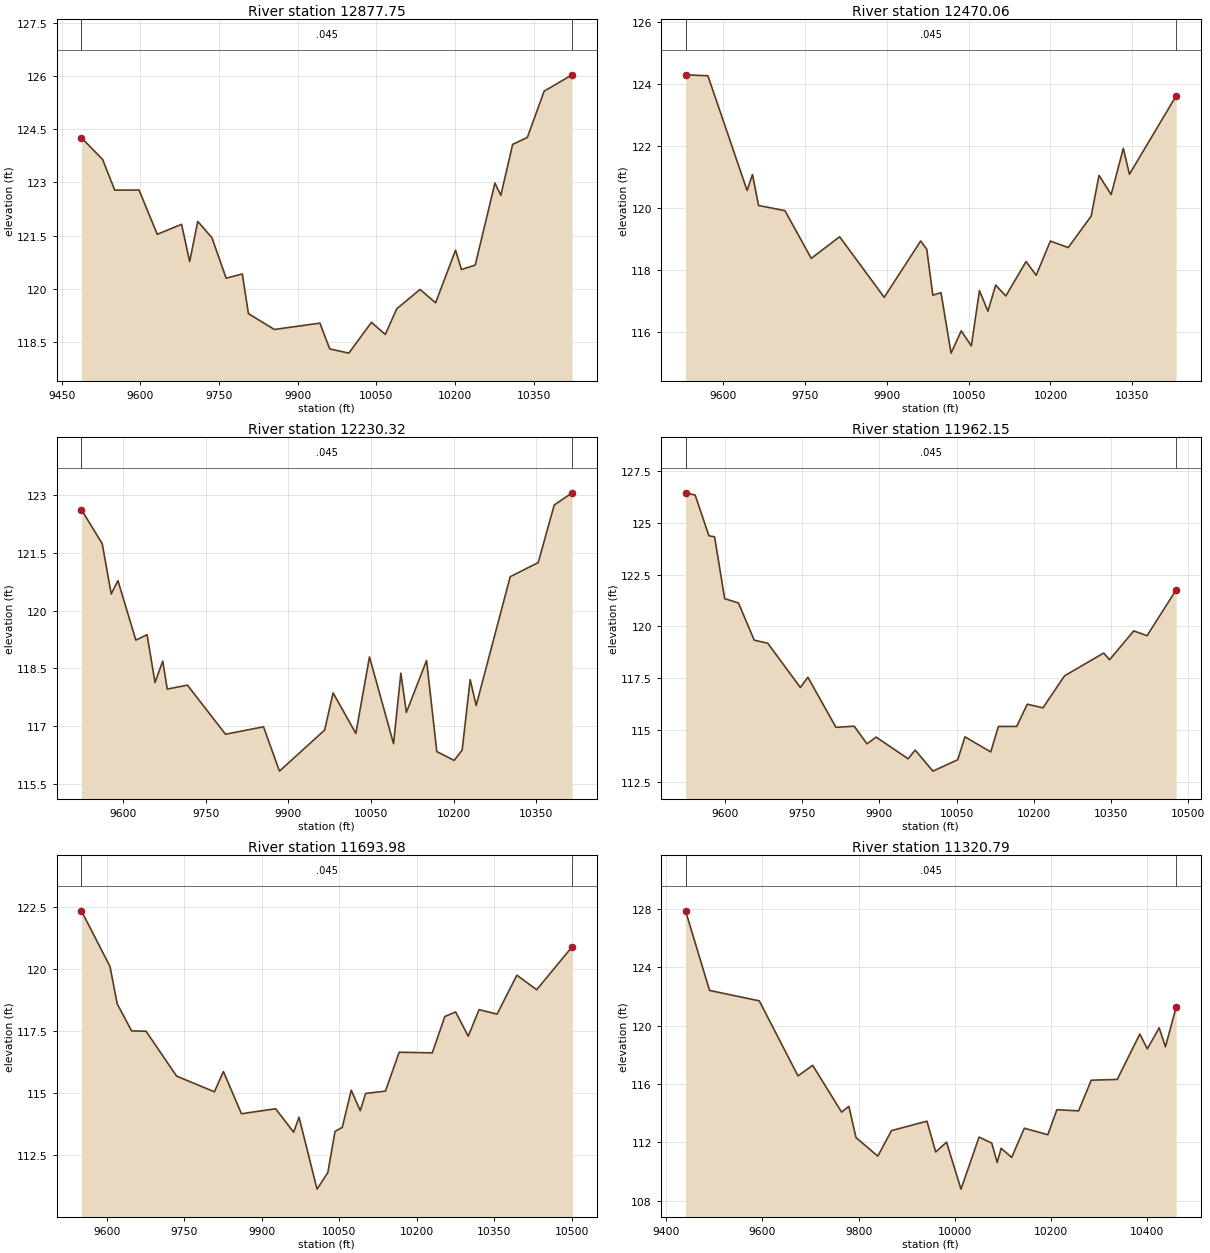
Type RM Length L Ch R = 1 ,12877.75,407.690000,407.690000,407.690000
XS GIS Cut Line= 6
1232545.81395879623202.1901519891232219.49079189  622999.2882559
 1232168.2498543622964.5752670621232132.95455188622945.558000162
1232030.45188114622897.3019884081231736.78618106622733.440152004
#Sta/Elev= 30
9487.594124.2597 9527.91123.6497 9551.06122.7826 9597.45122.7856 9632.22121.5365
 9678.58121.81639694.033 120.7689709.487121.8993 9736.53121.43899763.573120.2973
 9794.48120.4162 9806.07119.29779855.513118.84979942.519119.02869961.152118.3015
9997.634 118.18210040.79119.050710067.21 118.70910089.07119.433910133.56119.9796
10163.13119.602110201.19121.087410212.46120.541210238.76120.667510276.33122.9822
 10287.6122.636810310.14124.0742 10338.2124.270310370.26125.576310423.44126.0372
#Mann= 3 , 0 , 0
9487.594   0.045       09487.594   0.045       010423.44   0.045       0
#XS Ineff= 2 , 0
       0                               0
Bank Sta=9487.594,10423.44
Exp/Cntr=0.3,0.1

Type RM Length L Ch R = 1 ,12470.06,239.740600,239.740600,239.740600
XS GIS Cut Line= 2
1232797.11604217 622890.124179781232002.84520882622469.117235333
#Sta/Elev= 30
9531.469124.28689572.436124.25699644.232120.56539654.127121.07659665.267120.0815
9713.539 119.9169761.811118.37989813.796119.07569895.487117.12659962.325 118.939
9973.465 118.6739984.604117.19369999.457117.277810018.02115.329810036.59116.0467
10055.16115.563410070.01117.341410085.57116.680210099.71117.520310118.28117.1688
10155.41118.277210173.98117.836110199.97118.936810232.68118.727410274.72119.7396
10289.09121.049710311.37120.432610333.65121.921910344.79121.086510430.42123.6088
#Mann= 3 , 0 , 0
9531.469   0.045       09531.469   0.045       010430.42   0.045       0
#XS Ineff= 2 , 0
       0                               0
Bank Sta=9531.469,10430.42
Exp/Cntr=0.3,0.1

Type RM Length L Ch R = 1 ,12230.32,268.169700,268.169700,268.169700
XS GIS Cut Line= 6
1232834.00840327622775.1068186761232587.48062554622594.551263094
1232495.46673661622495.5929297661232439.91118103622422.676263109
1232339.21673661622405.3151519891232108.31395882622295.940151989
#Sta/Elev= 30
9524.615 122.6189562.344121.7328 9578.61120.4305 9590.81120.77459623.344119.2316
9643.677119.37199658.095118.13159672.143118.68699680.305117.96059716.876118.0631
9786.009116.78859854.935116.98239883.843115.83169965.804116.8972 9981.17117.8626
10022.42116.810610047.16118.7955 10090.8116.544210104.12118.3725 10114.1117.3553
10150.73118.703810169.33116.338310200.79  116.1110215.32116.378610229.83118.2072
10240.72117.535510302.44120.876410353.26121.2437 10382.3122.736810414.66123.0542
#Mann= 3 , 0 , 0
9524.615   0.045       09524.615   0.045       010414.66   0.045       0
#XS Ineff= 2 , 0
       0                               0
Bank Sta=9524.615,10414.66
Exp/Cntr=0.3,0.1

Type RM Length L Ch R = 1 ,11962.15,268.169800,268.169800,268.169800
XS GIS Cut Line= 6
1233082.09713752622518.4843232941232956.99050018622443.658603004
1232832.41872297622379.7018663021232750.09119265622345.749046797
1232544.14614586622274.054535499 1232232.7932141622093.422971036
#Sta/Elev= 30
9523.434126.43269542.147126.32439568.907124.36349579.813124.3163 9599.49121.3373
 9626.25121.13149656.833119.34019683.215119.19149746.494 117.0619761.129117.5559
9815.633115.14399851.121115.19819875.964114.35019893.708114.67499955.831113.6304
9969.605 114.04710004.03113.035910052.24113.585110066.27114.688710116.35113.9597
10131.29115.185110166.78115.186710187.34116.2568 10217.8116.082110259.68117.6217
10335.83118.720210347.25118.398510394.23119.7875 10420.1119.5551 10476.6121.7595
#Mann= 3 , 0 , 0
9523.434   0.045       09523.434   0.045       0 10476.6   0.045       0
#XS Ineff= 2 , 0
       0                               0
Bank Sta=9523.434,10476.6
Exp/Cntr=0.3,0.1

Type RM Length L Ch R = 1 ,11693.98,373.196800,373.196800,373.196800
XS GIS Cut Line= 2
1233144.33826435622208.7005686761232250.24104214621887.520013109
#Sta/Elev= 30
9550.519122.32759605.831120.08449619.775118.58489647.664117.49429675.552117.4823
9734.816115.67369808.024 115.0439825.454115.85829860.315  114.169926.551114.3601
9961.412113.4179 9971.87114.019710006.73111.125410027.65111.792110041.59113.4501
10055.54113.609110072.97115.1062 10090.4114.283710100.86114.9761 10139.2 115.071
10165.77116.636310229.84116.610110254.24118.073810275.16118.257410299.56117.2806
10320.48118.350310355.34118.168410393.69119.738210432.03119.152210500.55120.8757
#Mann= 3 , 0 , 0
9550.519   0.045       09550.519   0.045       010500.55   0.045       0
#XS Ineff= 2 , 0
       0                               0
Bank Sta=9550.519,10500.55
Exp/Cntr=0.3,0.1

Type RM Length L Ch R = 1 ,11320.79,380.682900,380.682900,380.682900
XS GIS Cut Line= 2
1233391.73409769622013.3880686761232501.97715327621514.256124228
#Sta/Elev= 30
9440.024127.87119489.954 122.4179593.367121.70299673.836116.56389704.377117.2875
9764.566 114.0799779.613114.47799794.541112.33529839.802111.06459868.305112.8136
 9942.07113.45919960.179 111.347 9982.75112.020810012.84108.804910050.46112.3717
 10076.8111.954210088.08 110.632 10096.3111.602710118.18110.979910144.51112.9759
10193.41112.533110212.22114.244310257.36114.166310283.69116.268910337.71116.3198
10384.65119.428710400.31118.412610424.89119.855510437.93118.555210460.22121.2718
#Mann= 3 , 0 , 0
9440.024   0.045       09440.024   0.045       010460.22   0.045       0
#XS Ineff= 2 , 0
       0                               0
Bank Sta=9440.024,10460.22
Exp/Cntr=0.3,0.1

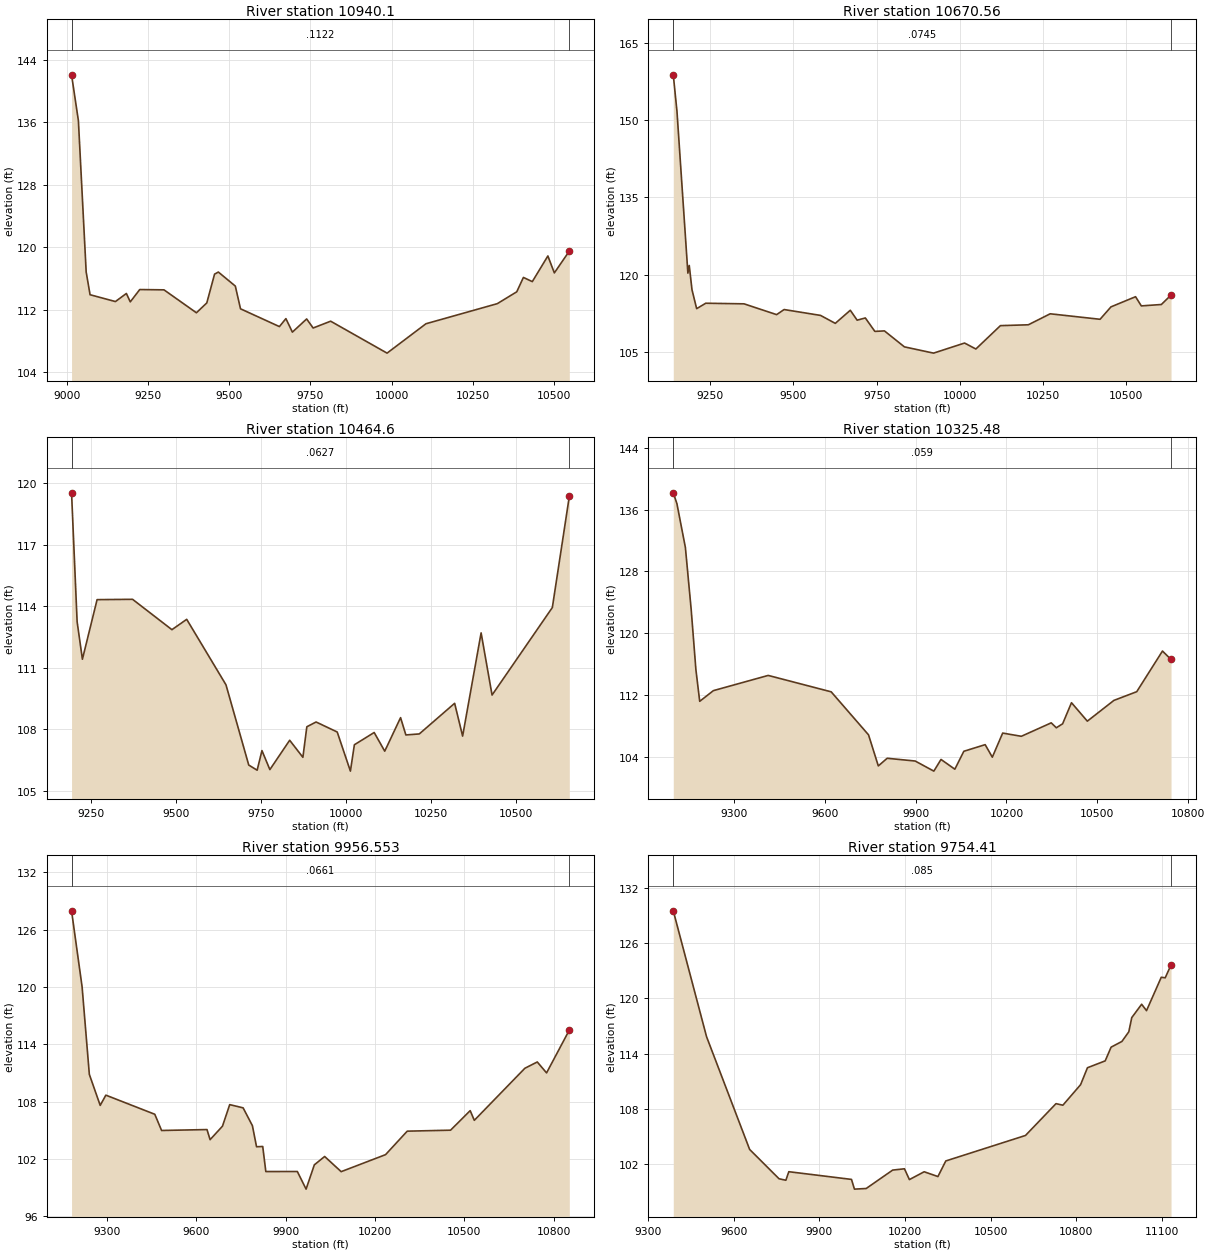
Type RM Length L Ch R = 1 , 10940.1,269.541000,269.541000,269.541000
XS GIS Cut Line= 2
1233755.92513672621952.9079671651232496.69369972621080.328506678
#Sta/Elev= 30
  9014.8142.05039035.869136.18889059.818116.82859071.793113.93129149.778113.0567
9183.556114.0903 9195.53113.01549224.661114.5924 9299.31 114.5549399.099111.6235
9431.031112.88129454.981116.56479466.591116.83019518.845 115.0369534.811112.1296
9654.558109.85559674.515110.87529694.473109.1478 9738.38110.83159758.338109.6752
9812.206 110.5469985.856106.4625 10105.6110.219110325.14112.787810385.01114.3035
10405.51116.141910432.91115.606410480.81118.886410500.76116.720810546.81119.5132
#Mann= 3 , 0 , 0
  9014.8  0.1122       0  9014.8  0.1122       010546.81  0.1122       0
#XS Ineff= 2 , 0
       0                               0
Bank Sta=9014.8,10546.81
Exp/Cntr=0.3,0.1

Type RM Length L Ch R = 1 ,10670.56,205.961500,205.961500,205.961500
XS GIS Cut Line= 2
1233878.71326438621819.6697860661232682.18214789620923.577705428
#Sta/Elev= 30
9139.191158.76679150.275151.68689183.066120.32459187.165121.81249195.363 117.113
9209.365113.43699236.731114.49029351.667114.37269449.495112.28119472.077113.2652
 9581.54112.12869625.747110.58979670.835 113.1279691.329111.20489715.923111.6365
9744.615109.02889773.307109.12669833.305106.03219920.867104.817610013.92106.7722
10047.93105.619510121.71110.145910205.48110.310510271.16112.441710420.93111.3769
10453.72113.7874 10527.5115.753910544.82113.971510605.02114.243910634.07116.0777
#Mann= 3 , 0 , 0
9139.191  0.0745       09139.191  0.0745       010634.07  0.0745       0
#XS Ineff= 2 , 0
       0                               0
Bank Sta=9139.191,10634.07
Exp/Cntr=0.3,0.1

Type RM Length L Ch R = 1 , 10464.6,139.120300,139.120300,139.120300
XS GIS Cut Line= 2
1233968.99104214 621561.999179781232732.01187548620776.408902019
#Sta/Elev= 30
9191.782119.53339208.187113.24019223.734111.41249266.953114.32049371.423114.3364
9487.263112.85489530.772113.35949646.376110.1647 9713.44106.24759738.171105.9973
9752.305106.95419775.625106.02619833.923107.45869872.805106.62619884.448108.1169
9911.654108.34949973.839107.8615 10012.7105.951810024.36107.238110082.66107.8366
10113.76106.925310160.39 108.56210175.94107.717310215.51107.767110319.54109.2618
10343.06107.661210397.47112.6988 10429.7109.664610607.17113.935610657.14119.3598
#Mann= 3 , 0 , 0
9191.782  0.0627       09191.782  0.0627       010657.14  0.0627       0
#XS Ineff= 2 , 0
       0                               0
Bank Sta=9191.782,10657.14
Exp/Cntr=0.3,0.1

Type RM Length L Ch R = 1 ,10325.48,368.929500,368.929500,368.929500
XS GIS Cut Line= 2
1234130.26992169 621485.313983471232730.25907099620625.839866534
#Sta/Elev= 30
9100.559138.15979112.534136.76369140.515131.08249159.764123.00059175.244115.2544
9187.785111.16319232.909112.54779413.847114.51739621.733112.39299744.925106.8245
9777.251   102.89806.521  103.799898.915 103.4349960.511102.12569984.191103.6386
10029.81102.374710059.44104.6941 10129.9105.552710153.51103.931210187.65107.0525
10249.24106.6356 10347.9108.376110364.73107.738510385.53 108.25510414.78 110.984
10467.05108.595310554.84111.2845 10630.1112.410610715.06117.674510743.34116.5832
#Mann= 3 , 0 , 0
9100.559   0.059       09100.559   0.059       010743.34   0.059       0
#XS Ineff= 2 , 0
       0                               0
Bank Sta=9100.559,10743.34
Exp/Cntr=0.3,0.1

Type RM Length L Ch R = 1 ,9956.553,202.142200,202.142200,202.142200
XS GIS Cut Line= 2
1234411.92890939 621083.535721571232829.66812548620545.070009753
#Sta/Elev= 30
9180.767127.96269216.216120.00159240.475110.85089276.976 107.6079295.925108.6783
 9460.28106.67699483.068104.98179635.555105.07699645.952104.01999687.539105.4324
9711.799107.68689756.852107.34889788.042105.48199801.905103.28059822.698 103.306
9833.095100.68419938.908 100.6899968.25498.845689995.979 101.38710030.63102.2596
10086.08 100.67310235.11102.452910307.88104.910310453.44105.012310519.29107.0581
10533.15106.043810702.96111.491510744.55112.149210775.74111.005110852.14115.4859
#Mann= 3 , 0 , 0
9180.767  0.0661       09180.767  0.0661       010852.14  0.0661       0
#XS Ineff= 2 , 0
       09707.309        10155.99       0
Bank Sta=9180.767,10852.14
Exp/Cntr=0.3,0.1

Type RM Length L Ch R = 1 , 9754.41,139.489900,139.489900,139.489900
XS GIS Cut Line= 3
1234407.78686544 620965.487469361233701.56837419620745.959140703
1232744.75622478620433.234823465
#Sta/Elev= 30
9387.163129.47949503.861115.84659655.031103.63059758.102100.45429782.152100.2915
9792.459101.217610012.34100.382610022.6599.3300110063.8899.3969310156.78101.3923
 10198.2 101.53210215.46100.361710267.23101.210710315.56100.693210343.17102.3821
10622.75105.143410729.75108.589710753.91 108.42210816.04110.644210840.13112.4819
10902.33113.222810923.04114.710810961.01115.329210985.17 116.37610995.53117.9119
11030.22119.3588 11047.3118.665411099.07122.282611112.88122.223611133.34123.6255
#Mann= 3 , 0 , 0
9387.163   0.085       09387.163   0.085       011133.34   0.085       0
#XS Ineff= 2 , 0
       09832.788        10227.95       0
Bank Sta=9387.163,11133.34
Exp/Cntr=0.3,0.1

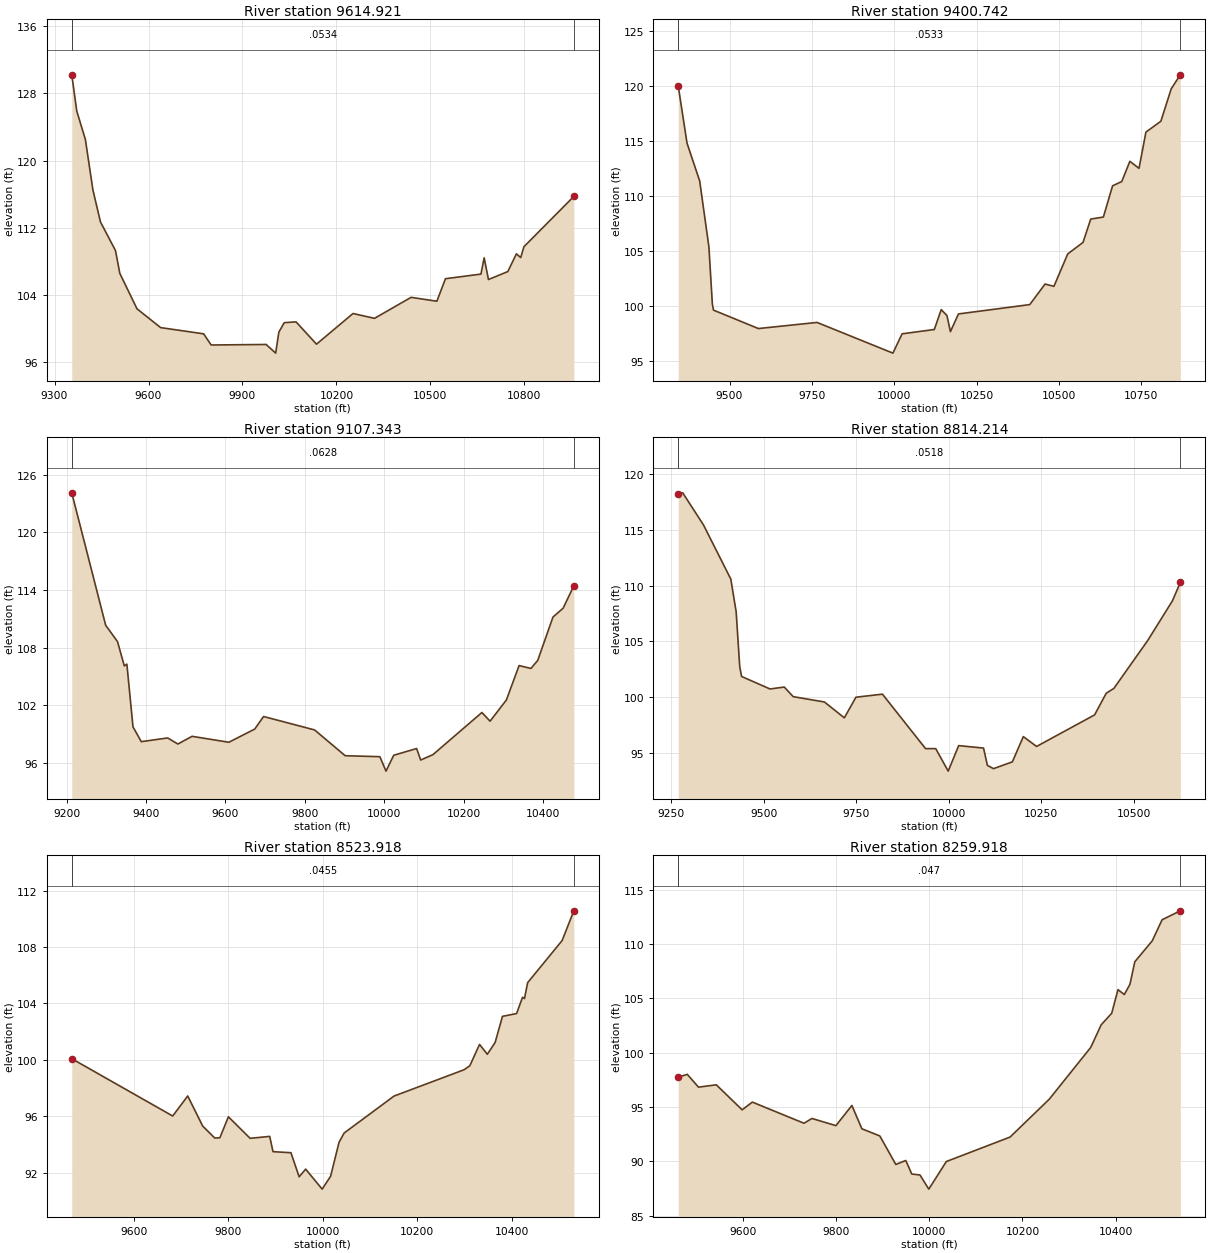
Type RM Length L Ch R = 1 ,9614.921,214.178400,214.178400,214.178400
XS GIS Cut Line= 2
1234521.69307375620886.7886345541232989.13681707620416.666647732
#Sta/Elev= 30
 9354.95 130.2039371.028125.88029398.481122.50449422.503116.50479446.525112.7184
 9494.57109.30459508.297106.60289563.204102.38359638.702 100.1459775.971 99.4065
9799.99398.077749975.59998.14069 10005.997.1114810016.1999.6141610033.35 100.732
 10071.1100.8281 10136.398.1747410252.98101.821210321.62101.247310438.29103.7442
10520.66103.283210548.11105.959510661.36 106.50810671.65 108.44510685.38105.8619
10747.15106.8079 10774.6 108.92110788.33108.470910798.63109.763210957.99115.7453
#Mann= 3 , 0 , 0
 9354.95  0.0534       0 9354.95  0.0534       010957.99  0.0534       0
#XS Ineff= 2 , 0
       09866.028                       0
Bank Sta=9354.95,10957.99
Exp/Cntr=0.3,0.1

Type RM Length L Ch R = 1 ,9400.742,293.399000,293.399000,293.399000
XS GIS Cut Line= 2
1234561.00493103620711.3047353181233128.71326435620190.471402004
#Sta/Elev= 30
9344.318120.00799371.084114.79189409.485111.35529437.413105.35539447.886100.1538
9451.377 99.59319587.52797.914629765.56998.471679995.97695.67618 10023.997.43474
10121.6597.82751 10142.699.6389710160.0599.0981210170.5397.6317410194.96 99.2451
10411.41100.096610457.87101.969810484.72101.757410526.61104.709310573.07  105.76
10596.43107.884710634.83108.070410662.76110.913910690.69111.306110715.13113.1446
10743.05 112.505   10764115.806910809.38116.7964 10840.8119.748710868.37121.0225
#Mann= 3 , 0 , 0
9344.318  0.0533       09344.318  0.0533       010868.37  0.0533       0
#XS Ineff= 2 , 0
       0 9835.28                       0
Bank Sta=9344.318,10868.37
Exp/Cntr=0.3,0.1

Type RM Length L Ch R = 1 ,9107.343,293.128800,293.128800,293.128800
XS GIS Cut Line= 2
1234611.35215327620704.7943186611233639.12993106619897.502651989
#Sta/Elev= 30
9213.226124.0956 9298.57110.33219328.421108.62599345.479106.09999351.924106.2905
9367.33199.772059388.12398.231579454.63798.617169480.31697.986579516.057 98.7865
9608.708 98.17029673.84199.543019696.014100.84619824.40699.450779901.441 96.7699
9988.74796.6696210004.1595.1687810023.53 96.816410081.1997.5163410091.4696.32259
10122.2796.8814510245.53101.262910266.07100.359510307.16102.563710339.09106.1397
10368.95 105.843   10386 106.67510424.38111.181710449.97112.104510476.92114.4382
#Mann= 3 , 0 , 0
9213.226  0.0628       09213.226  0.0628       010476.92  0.0628       0
#XS Ineff= 2 , 0
       09732.966                       0
Bank Sta=9213.226,10476.92
Exp/Cntr=0.3,0.1

Type RM Length L Ch R = 1 ,8814.214,290.296400,290.296400,290.296400
XS GIS Cut Line= 2
1234802.32437551620631.0095964521233808.40076435 619706.53042978
#Sta/Elev= 30
9268.507118.21929280.633118.31729336.709115.44449410.698110.5882 9425.15107.6519
9434.784102.74239439.764101.86489516.677 100.7459555.214100.9166  9579.3100.0569
9663.79699.577999717.56498.158729748.928100.00649820.619100.28019937.11595.40133
9964.67895.398639998.39893.3843610026.7395.6694810093.9495.4490310104.3893.89784
10120.8293.6061610171.8294.2132410201.4796.4758210237.3295.5950510394.1498.42076
10425.51 100.354 10446.4100.800110537.52 105.07410604.73108.646710625.91110.2897
#Mann= 3 , 0 , 0
9268.507  0.0518       09268.507  0.0518       010625.91  0.0518       0
#XS Ineff= 2 , 0
       09787.349                       0
Bank Sta=9268.507,10625.91
Exp/Cntr=0.3,0.1

Type RM Length L Ch R = 1 ,8523.918,264.000000,264.000000,264.000000
XS GIS Cut Line= 6
1234789.86502552 620105.397411011234675.77757645620015.703910362
1234574.81672048619954.7216158431234335.34329183 619862.67252147
1234163.04983959619780.5671593681233880.00819603619570.876901277
#Sta/Elev= 30
9468.216100.07599682.05196.012169713.87297.433389745.53195.303219771.01994.45349
9781.94294.46946 9800.0395.956359846.05494.430539887.57994.56803  9894.593.48535
9932.56593.408729949.86791.701969963.70992.247139998.65490.8281810016.5791.74365
10034.4894.1528310045.2394.8068510150.9397.4265610299.3999.2942910311.4799.57527
10332.08101.089910348.57100.391610365.06101.224810380.66103.079710410.52103.2758
10423.11104.430210427.31104.342810433.95105.465810507.06 108.45710531.83110.5614
#Mann= 3 , 0 , 0
9468.216  0.0455       09468.216  0.0455       010531.83  0.0455       0
#XS Ineff= 2 , 0
       0                               0
Bank Sta=9468.216,10531.83
Exp/Cntr=0.3,0.1

Type RM Length L Ch R = 1 ,8259.918,759.763900,759.763900,759.763900
XS GIS Cut Line= 6
1234874.01255814620004.9222814971234806.16765951619932.783508287
1234751.24525415619879.9602819981234509.15896706619673.334833914
1234373.95138907619553.4029480141234077.60513154619278.884476018
#Sta/Elev= 30
 9460.8997.756239480.391 98.00889504.33596.832629542.64697.048859598.12494.74626
9620.01695.45729 9730.9893.512929748.12393.952139799.49893.292739833.839 95.1468
9855.26893.00348 9893.8492.343619928.12689.722439949.55590.086659962.44588.84158
9980.07388.75374    999987.4525610036.6889.9906310173.5192.2414710257.72 95.7253
 10346.7100.483710369.25102.5692 10391.8103.630410405.32105.801710418.85105.3527
   10431106.2932 10441.4108.365610478.82110.289510500.02112.230310539.13113.0525
#Mann= 3 , 0 , 0
 9460.89   0.047       0 9460.89   0.047       010539.13   0.047       0
#XS Ineff= 2 , 0
       0                               0
Bank Sta=9460.89,10539.13
Exp/Cntr=0.3,0.1

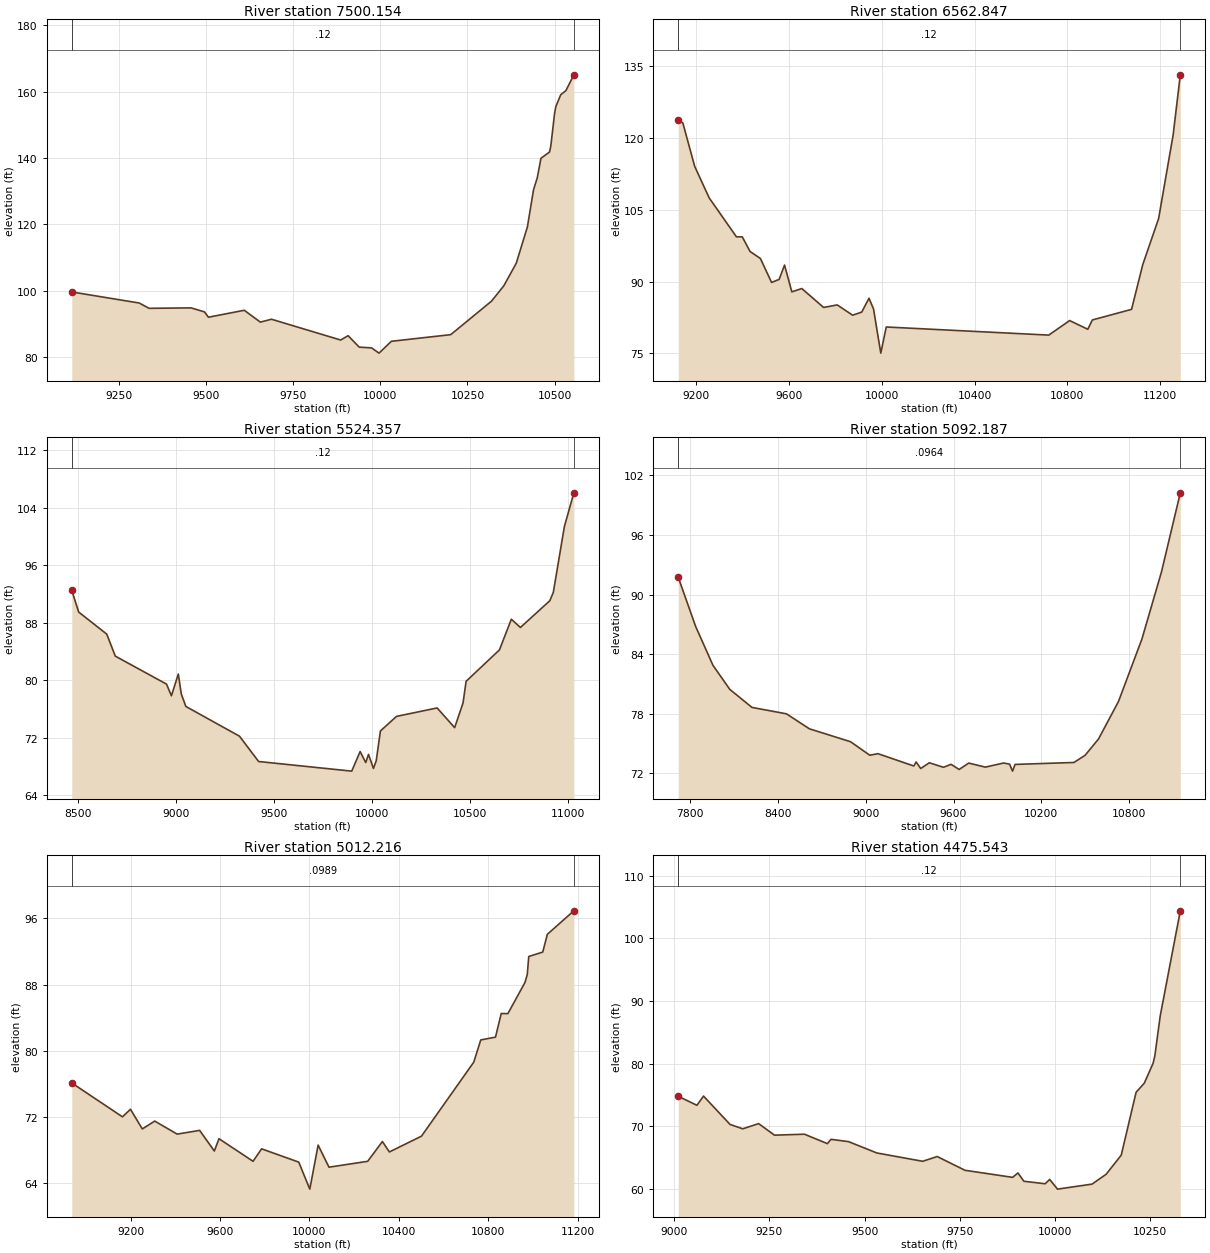
Type RM Length L Ch R = 1 ,7500.154,937.306600,937.306600,937.306600
XS GIS Cut Line= 2
1235431.66465327620066.7734853181234884.78965324618734.308207542
#Sta/Elev= 30
9115.01899.619899308.43196.282769336.80294.68124 9457.3894.812969495.60393.61163
 9507.0391.996119609.87694.089289655.97990.520789687.89791.388239886.49685.11277
9907.77486.427359939.69282.966139975.15682.746129996.43481.16497 10031.984.73523
10202.1386.7359610319.1696.8395410354.62101.504310390.09 108.274   10422119.1887
10439.74130.468610450.37134.026510461.01139.937610485.84141.852110489.39 143.731
10500.02153.412310503.57155.504410517.76159.1166 10532.5160.343110555.34165.1166
#Mann= 3 , 0 , 0
9115.018    0.12       09115.018    0.12       010555.34    0.12       0
#XS Ineff= 2 , 0
       0                               0
Bank Sta=9115.018,10555.34
Exp/Cntr=0.3,0.1

Type RM Length L Ch R = 1 ,6562.847,1038.490800,1038.490800,1038.490800
XS GIS Cut Line= 2
1236464.65076435620249.0651520041235284.09520879 618434.82904087
#Sta/Elev= 30
9122.243123.74329142.207123.10799193.093114.06479255.721107.4579 9373.1599.33557
9398.34499.329759431.86496.274579476.54494.807559524.66689.809039557.12190.43117
9580.60793.437789611.92187.841099654.97988.530319748.92184.583499807.63685.11036
9874.17982.962159913.32283.611849944.63686.501769964.20784.262879995.52275.04236
10019.0180.5008310719.6678.8054610809.6981.8434110887.9880.0231210907.5581.96908
11076.6284.1834111124.75 93.508511193.29103.148411255.92 120.62511286.77133.1684
#Mann= 3 , 0 , 0
9122.243    0.12       09122.243    0.12       011286.77    0.12       0
#XS Ineff= 2 , 0
       0                               0
Bank Sta=9122.243,11286.77
Exp/Cntr=0.3,0.1

Type RM Length L Ch R = 1 ,5524.357,432.170100,432.170100,432.170100
XS GIS Cut Line= 3
1237535.16244408 619468.409338311236972.85204586618817.313087732
1235410.87871745618149.775012672
#Sta/Elev= 30
8469.32892.481788504.68489.465728647.73986.394228691.14983.335778952.16279.44338
 8977.2677.818189012.39680.842949027.45578.075289050.89476.33259    932472.19803
 9421.6868.672389896.20967.335539939.02370.060479967.566 68.52839981.83869.66243
10006.8167.7073710021.0868.7693210042.4972.9240110124.5574.9518610331.4976.12486
10420.7973.38766 10463.576.8163810479.23 79.833710649.0384.1991210709.6988.46498
10756.0787.3237110905.9291.0428610923.7692.2207610980.14101.373611028.27106.0552
#Mann= 3 , 0 , 0
8469.328    0.12       08469.328    0.12       011028.27    0.12       0
#XS Ineff= 2 , 0
       0                10221.95       0
Bank Sta=8469.328,11028.27
Exp/Cntr=0.3,0.1

Type RM Length L Ch R = 1 ,5092.187,79.971100,79.971100,79.971100
XS GIS Cut Line= 6
1238820.91312075619195.4750514631238439.46279213619096.824104398
1237850.06743103618865.3845964371237225.06743106 618644.03042978
1236209.44243103618305.4887630941235565.43186787618113.602998748
#Sta/Elev= 30
7717.41691.748287836.32786.798867954.93482.880938070.15380.458268221.75178.64498
8457.685 77.99848614.04876.493628895.797 75.19119027.44473.832139083.13273.98945
  9328.272.748889344.17173.155139375.49672.496749434.466 73.07319531.19672.61853
9583.01672.91809 9638.2972.399259703.83173.042119817.54372.634579941.59273.04545
 9982.9772.9395510003.6872.2325110020.9372.9066210423.2473.1034810499.4473.82081
10591.5175.46846 10727.979.2393510888.1785.5203211022.0392.2860911150.75100.2422
#Mann= 3 , 0 , 0
7717.416  0.0964       07717.416  0.0964       011150.75  0.0964       0
#XS Ineff= 2 , 0
       0                10400.59       0
Bank Sta=7717.416,11150.75
Exp/Cntr=0.3,0.1

Type RM Length L Ch R = 1 ,5012.216,536.672800,536.672800,536.672800
XS GIS Cut Line= 3
1237693.00395939618754.8341546211237423.35803744618636.453018144
1235575.29696256 618008.37532188
#Sta/Elev= 30
8936.68476.129839163.50272.041699199.33372.952739252.35870.58201  9307.871.52857
9408.28969.957589508.778 70.40619574.61567.918499595.40669.400159747.872 66.6775
9785.98868.181379952.315 66.576110001.7263.3193110038.9468.6317610087.4565.96746
10260.7166.6737710326.5569.0644410357.73 67.804410501.3269.7092810735.4378.64637
10766.6281.3225610832.4681.6562610858.1784.50947 10887.984.4935210964.1388.24123
10974.5389.1893210981.4691.3908511043.8391.9202311064.6294.0705511183.0596.89939
#Mann= 3 , 0 , 0
8936.684  0.0989       08936.684  0.0989       011183.05  0.0989       0
#XS Ineff= 2 , 0
       0                10408.23       0
Bank Sta=8936.684,11183.05
Exp/Cntr=0.3,0.1

Type RM Length L Ch R = 1 ,4475.543,499.603400,499.603400,499.603400
XS GIS Cut Line= 2
 1237666.6970402618659.4715724591236736.08977291617725.575940311
#Sta/Elev= 30
9010.56974.802469059.62473.362629076.96174.832759146.68170.309929180.04669.61239
9221.73170.439499263.41668.597819341.89768.753529402.32167.246469411.61767.93685
9457.94467.562919532.05165.762059652.47364.430629690.49865.192419763.632 62.9961
9888.68761.869679902.58262.57591 9918.2561.247289974.02660.848819985.95161.53775
10006.5659.9926710097.1160.7914610134.1662.3585110173.8965.41636 10212.975.44322
10234.3176.8825910257.5580.06641 10262.281.2919610276.1587.5962610328.97104.3811
#Mann= 3 , 0 , 0
9010.569    0.12       09010.569    0.12       010328.97    0.12       0
#XS Ineff= 2 , 0
       0                               0
Bank Sta=9010.569,10328.97
Exp/Cntr=0.3,0.1

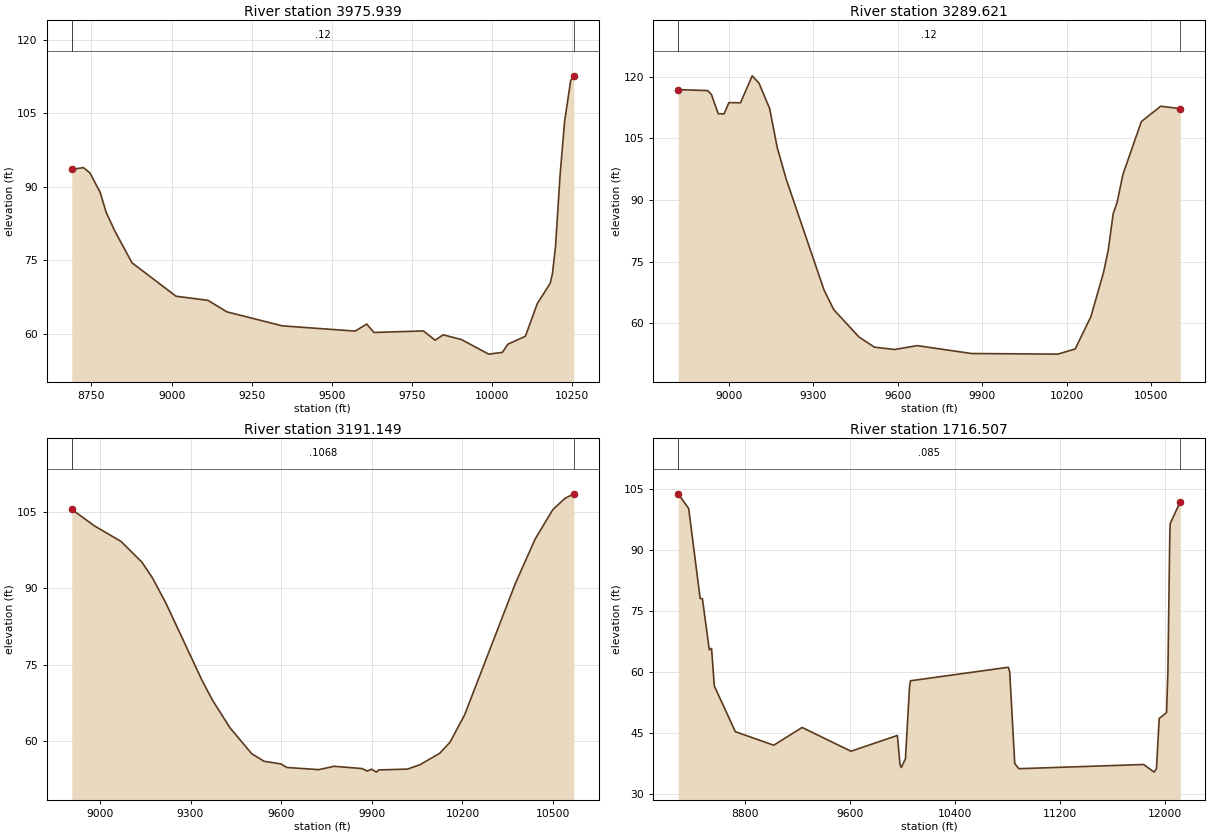
Type RM Length L Ch R = 1 ,3975.939,686.318000,686.318000,686.318000
XS GIS Cut Line= 2
1238232.29580331618573.9740850031237147.13538569617442.776558757
#Sta/Elev= 30
8688.43293.567598724.82493.935228745.40592.827778777.229 88.85968795.41584.87246
8822.69381.00154 8876.4874.496419013.91867.66845 9113.6666.824739172.763  64.475
9345.66561.613829573.14860.545919609.21461.977639631.94660.264079786.41460.57591
9822.89358.682039848.02459.778269904.728 58.82349990.20155.8404110032.8556.19934
10050.21 57.878210104.7759.4923710141.8666.1616610182.0670.2882310189.2572.31314
10198.7377.7975410212.9592.3757810227.16103.396110246.12111.724610255.97112.6831
#Mann= 3 , 0 , 0
8688.432    0.12       08688.432    0.12       010255.97    0.12       0
#XS Ineff= 2 , 0
       0                               0
Bank Sta=8688.432,10255.97
Exp/Cntr=0.3,0.1

Type RM Length L Ch R = 1 ,3289.621,98.472200,98.472200,98.472200
XS GIS Cut Line= 2
1238965.63178509617564.5825452951237268.22952172617017.360323071
#Sta/Elev= 30
8820.773116.86428924.876116.62958938.664115.69088962.794111.01598983.477110.9502
9000.712113.69789042.078113.66329083.443120.21789107.573118.45399145.491112.2716
9172.216102.83769204.09295.13593 9338.5368.171899373.00163.375939462.62656.71659
 9517.7854.239169589.22153.663819669.453 54.61189862.49152.6892810169.2852.54248
10230.7753.7955610286.49 61.6488 10331.372.3378110348.3877.8994310365.77 86.7057
10379.5689.3835210400.2496.1926610465.74109.088110534.68112.8309 10604.2112.2263
#Mann= 3 , 0 , 0
8820.773    0.12       08820.773    0.12       0 10604.2    0.12       0
#XS Ineff= 2 , 0
       0                               0
Bank Sta=8820.773,10604.2
Exp/Cntr=0.3,0.1

Type RM Length L Ch R = 1 ,3191.149,1474.642500,1474.642500,1474.642500
XS GIS Cut Line= 4
1238953.92167991617444.7979278711238266.62858438617234.616553083
1237869.38578603617123.2204244431237362.84867278616965.584393352
#Sta/Elev= 30
8906.922105.44838981.133102.23449070.33499.145639138.95195.113499173.25992.09236
9217.85987.157599337.25172.061989372.24668.12126 9430.5762.674049502.61757.58985
9543.78756.10874 9598.6855.601859619.265 54.90099724.93854.480789775.02455.13211
9868.04854.690669885.08554.195869898.71554.569579915.75153.991749922.56654.41914
10017.9754.5832710059.0455.4317910124.3257.6607110158.6859.8349610206.7865.14895
10375.1590.9293910440.4499.6116810498.85105.367310538.82107.5727 10568.7108.4801
#Mann= 3 , 0 , 0
8906.922  0.1068       08906.922  0.1068       0 10568.7  0.1068       0
#XS Ineff= 2 , 0
       0                               0
Bank Sta=8906.922,10568.7
Exp/Cntr=0.3,0.1

Type RM Length L Ch R = 1 ,1716.507,0.000000,0.000000,0.000000
XS GIS Cut Line= 2
1238941.67260489616616.5212156031235339.24204934615346.989965588
#Sta/Elev= 30
8295.649 103.775  8375.3100.15068462.26578.035888479.65877.962068531.83765.40519
 8549.2365.742218570.10256.497858730.11745.25007 9022.3241.928139237.99346.29056
9610.20340.443699962.83244.328739982.41337.306769992.44436.4336710024.16 38.5643
10055.4656.3681710062.4257.7755810806.8461.1071410817.2859.9933710855.5437.43062
10886.8536.1468311836.5137.1787511916.5235.3035911933.9136.1808811954.7848.49411
12010.4449.9469212020.8760.0621812034.7992.6204512038.2796.4579212115.23 101.864
#Mann= 3 , 0 , 0
8295.649   0.085       08295.649   0.085       012115.23   0.085       0
#XS Ineff= 2 , 0
       0                10701.07       0
Bank Sta=8295.649,12115.23
Exp/Cntr=0.3,0.1